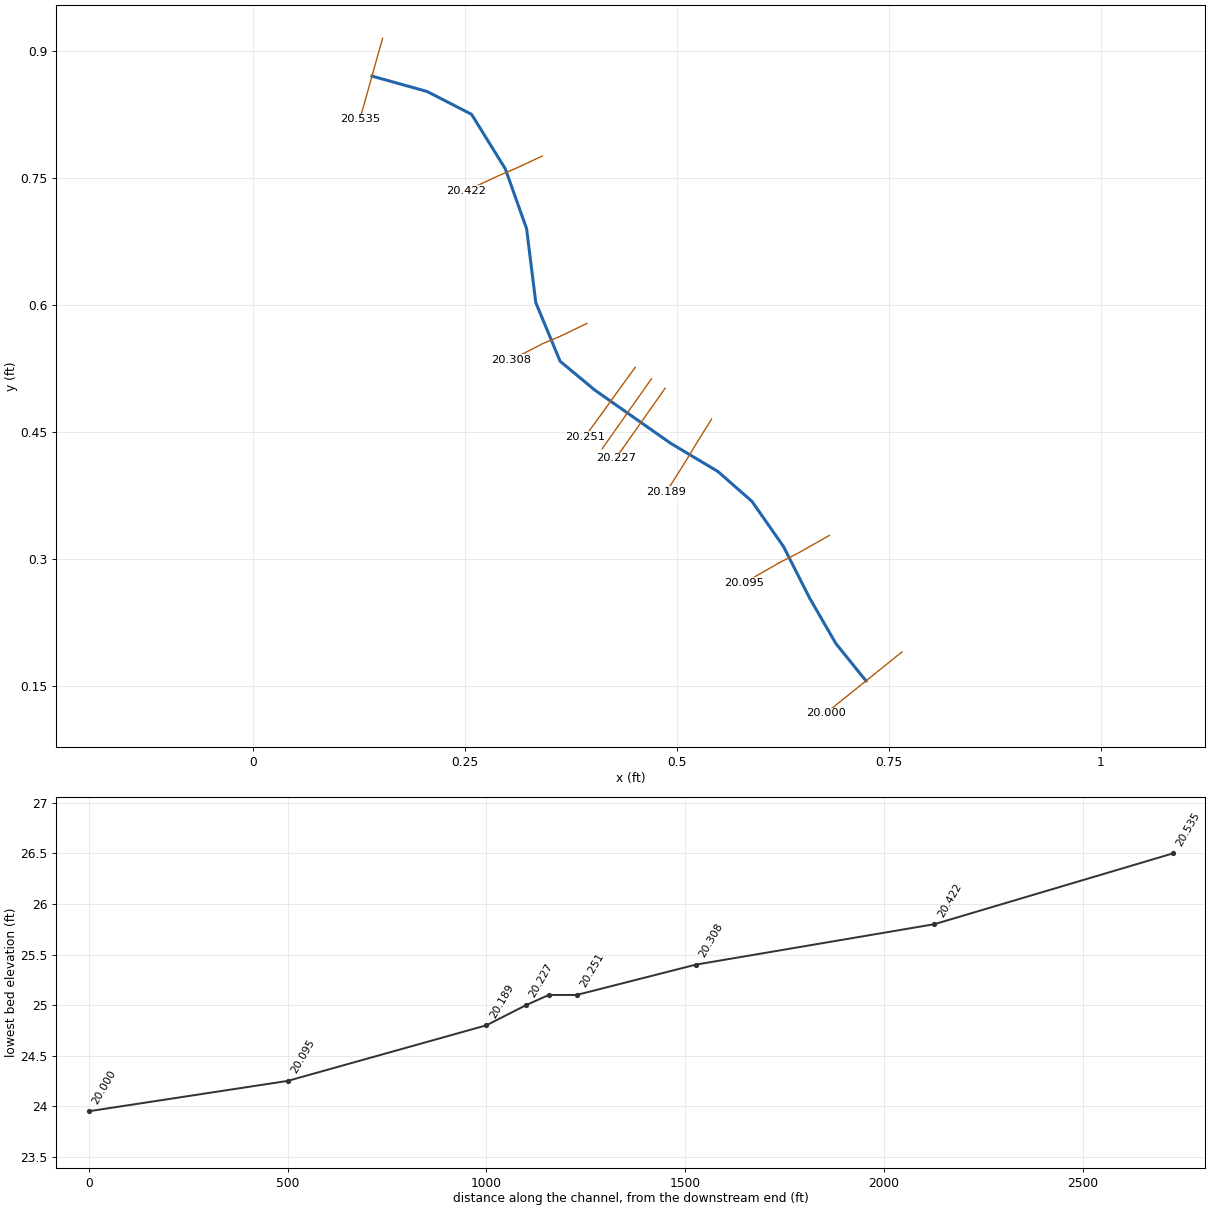
--- MULTCULV.prj (project) ---

Proj Title=Multiple Culverts - Example 4
Current Plan=p01
Default Exp/Contr=0.3,0.1
English Units
Geom File=g01
Flow File=f01
Plan File=p01
Y Axis Title=Elevation
X Axis Title(PF)=Main Channel Distance
X Axis Title(XS)=Station
BEGIN DESCRIPTION:
END DESCRIPTION:
DSS Export Rating Curves= 0
DSS Export Rating Curve Sorted= 0
DSS Export Volume Flow Curves= 0
DXF OffsetX= 0
DXF OffsetY= 0
DXF ScaleX= 1
DXF ScaleY= 10

--- MULTCULV.P01 (plan) ---

Plan Title=Spring Creek Multiple Culverts
Short Identifier=Mult Culvert
Geom File=g01
Flow File=f01
Interactive Comp Mode
Subcritical Flow
K Sum by GR=-1
Std Step Tol= 0.01
Critical Tol= 0.01
Num of Std Step Trials= 20
Max Error Tol= 0.3
Flow Tol Ratio= 0.001
Log Output Level= 0
Friction Slope Method= 1
Calc Critical at every XS
Parabolic Critical Depth
Global Vel Dist= 0 , 0 , 0
Global Log Level= 0
Encroach Param=-1 ,0,0, 0

--- MULTCULV.F01 (steady flow) ---

Flow Title=Multiple Culvert Flow Data
Number of Profiles= 3
Profile Names=5 yr        ,10 yr       ,25 yr
River Rch & RM=Spring Creek,Culvrt Reach,20.535
     250     400     600
Boundary for River Rch & Prof#=Spring Creek,Culvrt Reach, 1
Up Type= 0
Dn Type= 1
Dn Known WS=29.8
Boundary for River Rch & Prof#=Spring Creek,Culvrt Reach, 2
Up Type= 0
Dn Type= 1
Dn Known WS=31.2
Boundary for River Rch & Prof#=Spring Creek,Culvrt Reach, 3
Up Type= 0
Dn Type= 1
Dn Known WS=31.9

--- MULTCULV.g01 (geometry) ---

Geom Title=Multiple Culvert Geometry
Program Version=4.01

River Reach=Spring Creek    ,Culvrt Reach
Reach XY= 15
        0.140665       0.8705235       0.2055641       0.8523909
       0.2581144       0.8253638       0.2979215       0.7609329
       0.3230294       0.6902287       0.3338485       0.6029106
       0.3625866       0.5335277       0.4036228       0.4994463
       0.4930448       0.4365904       0.5486862       0.4033264
       0.5888717       0.3679834       0.6258661       0.3148688
       0.6568779       0.2536383       0.6878144       0.2000093
       0.7233385       0.1559252

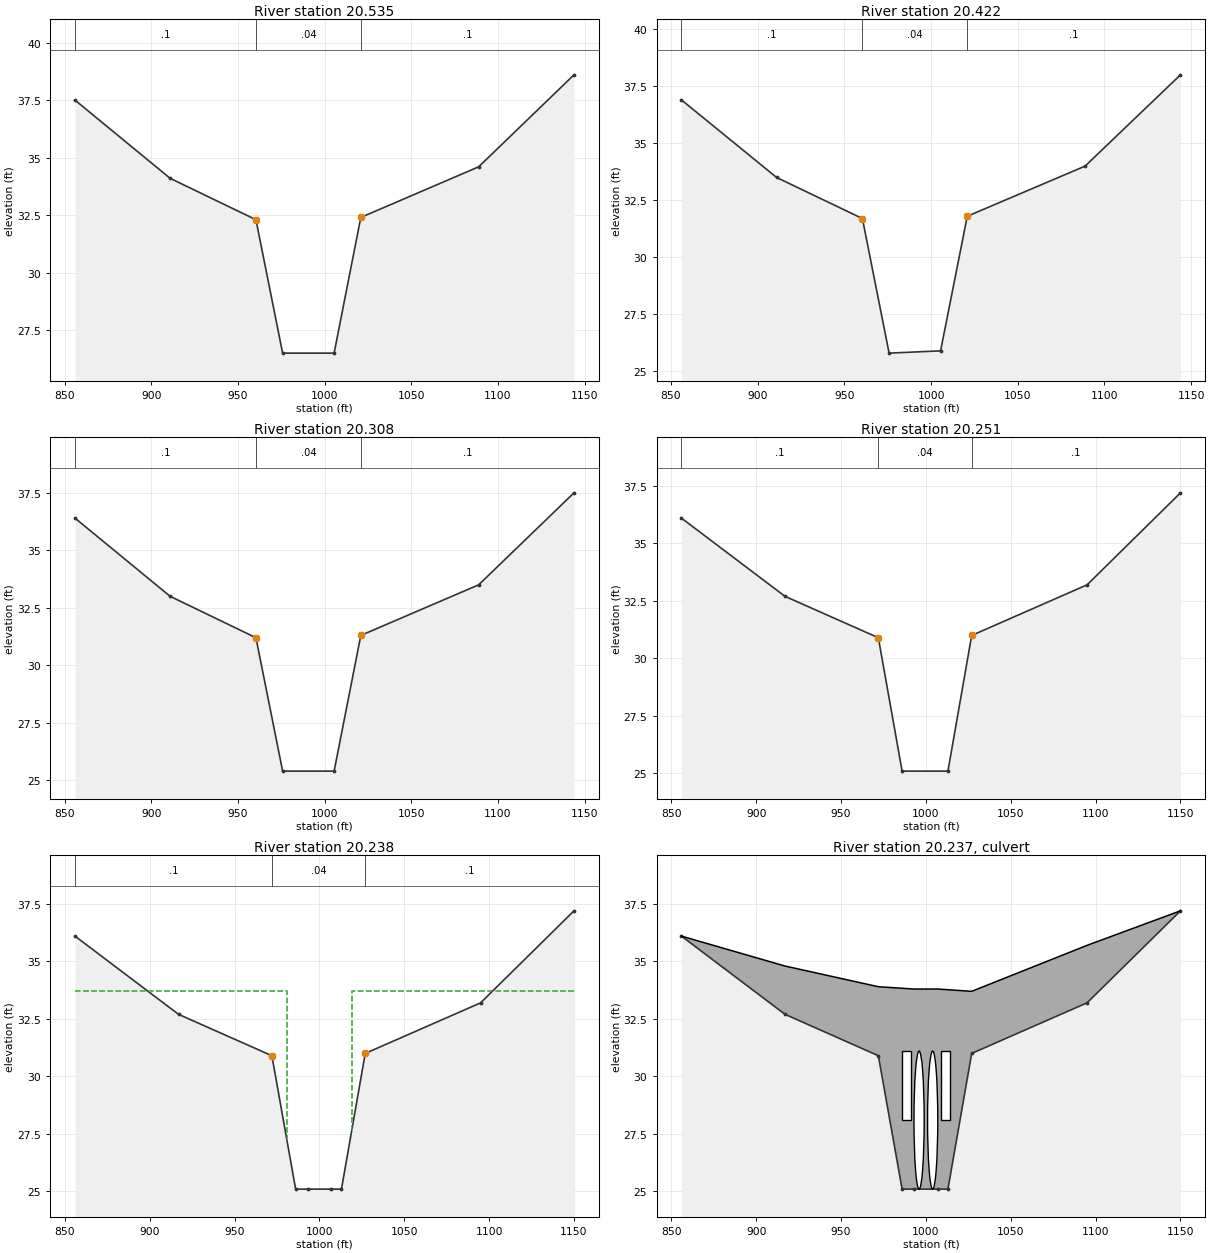
Type RM Length L Ch R = 1 ,20.535  ,650,600,500
BEGIN DESCRIPTION:
River mile 20.535 - Upstream Cross Section
END DESCRIPTION:
XS GIS Cut Line= 5
0.153138454378060.915167729896820.143467242306140.88055311536959
        0.140665       0.87052350.137862757693860.86049388463041
 0.1264685162507 0.8197123080863
#Sta/Elev= 8
     856    37.5   910.9    34.1   960.4    32.3   975.8    26.5  1005.5    26.5
  1020.9    32.4  1088.9    34.6  1143.9    38.6
#Mann= 3 , 0 , 0
     856      .1       0   960.4     .04       0  1020.9      .1       0
Bank Sta=960.4,1020.9
XS Rating Curve= 0 ,0
Exp/Cntr=0.3,0.1

Type RM Length L Ch R = 1 ,20.422  ,650,600,500
BEGIN DESCRIPTION:
River mile 20.422
END DESCRIPTION:
XS GIS Cut Line= 5
0.341554538208110.776055475898710.308953262838740.76092733238738
0.29937367589613 0.75684355222520.289794088953510.75275977206301
0.251419275855020.73486174303342
#Sta/Elev= 8
     856    36.9   910.9    33.5   960.4    31.7   975.8    25.8  1005.5    25.9
  1020.9    31.8  1088.9      34  1143.9      38
#Mann= 3 , 0 , 0
     856      .1       0   960.4     .04       0  1020.9      .1       0
Bank Sta=960.4,1020.9
XS Rating Curve= 0 ,0
Exp/Cntr=0.3,0.1

Type RM Length L Ch R = 1 ,20.308  ,300,300,350
BEGIN DESCRIPTION:
River mile 20.308
END DESCRIPTION:
XS GIS Cut Line= 5
0.394153425365370.578294596235140.361790686559750.56266267316702
  0.3521695950120.558677658256890.342548503464250.55469264334675
0.304940972862010.53523398549247
#Sta/Elev= 8
     856    36.4   910.9      33   960.4    31.2   975.8    25.4  1005.5    25.4
  1020.9    31.3  1088.9    33.5  1143.9    37.5
#Mann= 3 , 0 , 0
     856      .1       0   960.4     .04       0  1020.9      .1       0
Bank Sta=960.4,1020.9
XS Rating Curve= 0 ,0
Exp/Cntr=0.3,0.1

Type RM Length L Ch R = 1 ,20.251  ,70,70,70
BEGIN DESCRIPTION:
River mile 20.251
END DESCRIPTION:
XS GIS Cut Line= 5
 0.45117423531140.526398280340910.427647326326370.49413096005941
0.42220321099447 0.48638588471710.416759095662580.47864080937479
0.391767962189150.44445881160986
#Sta/Elev= 8
     856    36.1     917    32.7     972    30.9     986    25.1    1013    25.1
    1027      31    1095    33.2    1150    37.2
#Mann= 3 , 0 , 0
     856      .1       0     972     .04       0    1027      .1       0
Bank Sta=972,1027
XS Rating Curve= 0 ,0
Exp/Cntr=0.3,0.1

Type RM Length L Ch R = 1 ,20.238  ,57,57,57
BEGIN DESCRIPTION:
River mile 20.238 - Upstream end of culvert
END DESCRIPTION:
XS GIS Cut Line= 5
0.470326331870450.512943347931250.447362063561350.48027321194186
0.441917948229460.472528136599540.436473832897560.46478306125723
0.412123789776710.43014145154433
#Sta/Elev= 10
     856    36.1     917    32.7     972    30.9     986    25.1     993    25.1
    1007    25.1    1013    25.1    1027      31    1095    33.2    1150    37.2
#Mann= 3 , 1 , 0
     856      .1       0     972     .04       0    1027      .1       0
#XS Ineff= 2 , 0
             981    33.7    1019            33.7
Permanent Ineff=
       F       F
Bank Sta=972,1027
XS Rating Curve= 0 ,0
Exp/Cntr=0.5,0.3

Type RM Length L Ch R = 2 ,20.237  ,,,
BEGIN DESCRIPTION:
Twin Circular Pipe Crossing
END DESCRIPTION:
Bridge Culvert-0,0,1,-1, 0
Deck Dist Width WeirC Skew NumUp NumDn MinLoCord MaxHiCord MaxSubmerge Is_Ogee
10,40,2.6,0, 8, 8, 33.7, , 0.95, 0, 2,2,,
     856     917     972     993    1007    1027    1095    1150
    36.1    34.8    33.9    33.8    33.8    33.7    35.7    37.2
                                                                
     856     917     972     993    1007    1027    1095    1150
    36.1    34.8    33.9    33.8    33.8    33.7    35.7    37.2
                                                                
Multiple Barrel Culv=2,3,5,50,0.013,0.2,1,10,2,28.1,28, 2,Box         , 0 ,5
   988.5   988.5  1011.5  1011.5
Culvert Bottom n=0.013
Multiple Barrel Culv=1,6,,50,0.013,0.5,1,1,1,25.1,25, 2,Circular    , 0 ,5
     996     996    1004    1004
Culvert Bottom n=0.013
BC Design=,, 0 ,, 0 ,,,,,,
BC HTab HWMax=37.2
BC Use User HTab Curves=0
BC User HTab FreeFlow(D)= 0

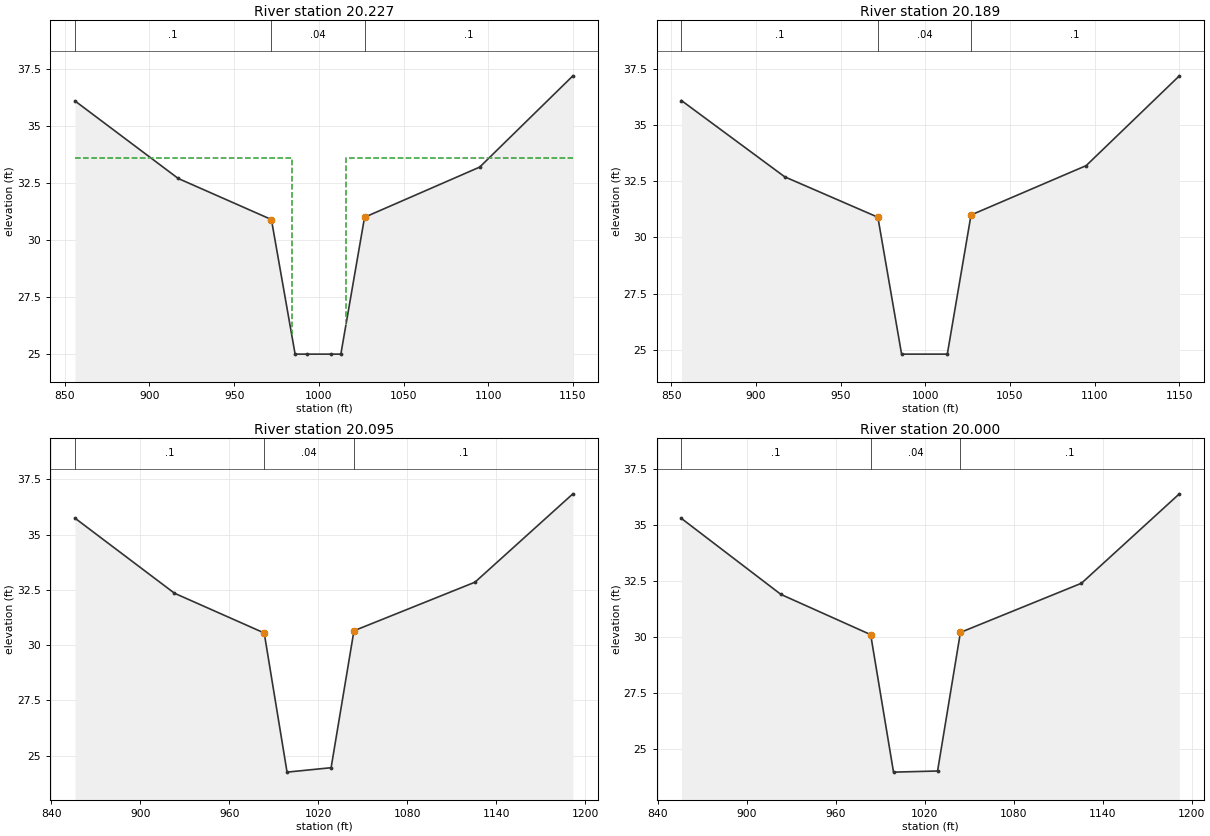
Type RM Length L Ch R = 1 ,20.227  ,100,100,100
BEGIN DESCRIPTION:
River mile 20.227 - Downstream end of culvert
END DESCRIPTION:
XS GIS Cut Line= 5
0.486379760761790.50165918160696 0.46341549245270.46898904561756
 0.45797137712080.46124397027524 0.45252726178890.45349889493293
0.428177218668050.41885728522003
#Sta/Elev= 10
     856    36.1     917    32.7     972    30.9     986      25     993      25
    1007      25    1013      25    1027      31    1095    33.2    1150    37.2
#Mann= 3 , 1 , 0
     856      .1       0     972     .04       0    1027      .1       0
#XS Ineff= 2 , 0
             984    33.6    1016            33.6
Permanent Ineff=
       F       F
Bank Sta=972,1027
XS Rating Curve= 0 ,0
Exp/Cntr=0.5,0.3

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
Type RM Length L Ch R = 1 ,20.189  ,600,500,550
BEGIN DESCRIPTION:
River mile 20.189
END DESCRIPTION:
XS GIS Cut Line= 5
0.541216833229950.46534175471975 0.5202014419748 0.4313851834127
0.515343679219880.423259500375440.510485916464960.41513381733818
0.487972215575050.37927159493454
#Sta/Elev= 8
     856    36.1     917    32.7     972    30.9     986    24.8    1013    24.8
    1027      31    1095    33.2    1150    37.2
#Mann= 3 , 0 , 0
     856      .1       0     972     .04       0    1027      .1       0
Bank Sta=972,1027
XS Rating Curve= 0 ,0
Exp/Cntr=0.3,0.1

Type RM Length L Ch R = 1 ,20.095  ,500,500,450
BEGIN DESCRIPTION:
River mile 20.095
END DESCRIPTION:
XS GIS Cut Line= 5
0.680186603091830.327782934737840.641950215853380.30615981303772
0.632660084517820.301454581250420.623369953182260.29674934946312
0.579221678946560.27159383973436
#Sta/Elev= 8
     856   35.75   923.1   32.35   983.6   30.55     999   24.25  1028.7   24.45
  1044.1   30.65  1125.7   32.85  1191.7   36.85
#Mann= 3 , 0 , 0
     856      .1       0   983.6     .04       0  1044.1      .1       0
Bank Sta=983.6,1044.1
XS Rating Curve= 0 ,0
Exp/Cntr=0.3,0.1

Type RM Length L Ch R = 1 ,20.000  ,0,0,0
BEGIN DESCRIPTION:
River mile 20.000 - Downstream Cross Section
END DESCRIPTION:
XS GIS Cut Line= 5
0.765650964955870.190021670980210.73144716178575 0.1624593679232
       0.7233385       0.15592520.71522983821425 0.1493910320768
0.675664936342810.11750861799619
#Sta/Elev= 8
     856    35.3   923.1    31.9   983.6    30.1     999   23.95  1028.7      24
  1044.1    30.2  1125.7    32.4  1191.7    36.4
#Mann= 3 , 0 , 0
     856      .1       0   983.6     .04       0  1044.1      .1       0
Bank Sta=983.6,1044.1
XS Rating Curve= 0 ,0
Exp/Cntr=0.3,0.1

Chan Stop Cuts=-1
Use User Specified Reach Order=0
User Specified Reach Order=Spring Creek    ,Culvrt Reach